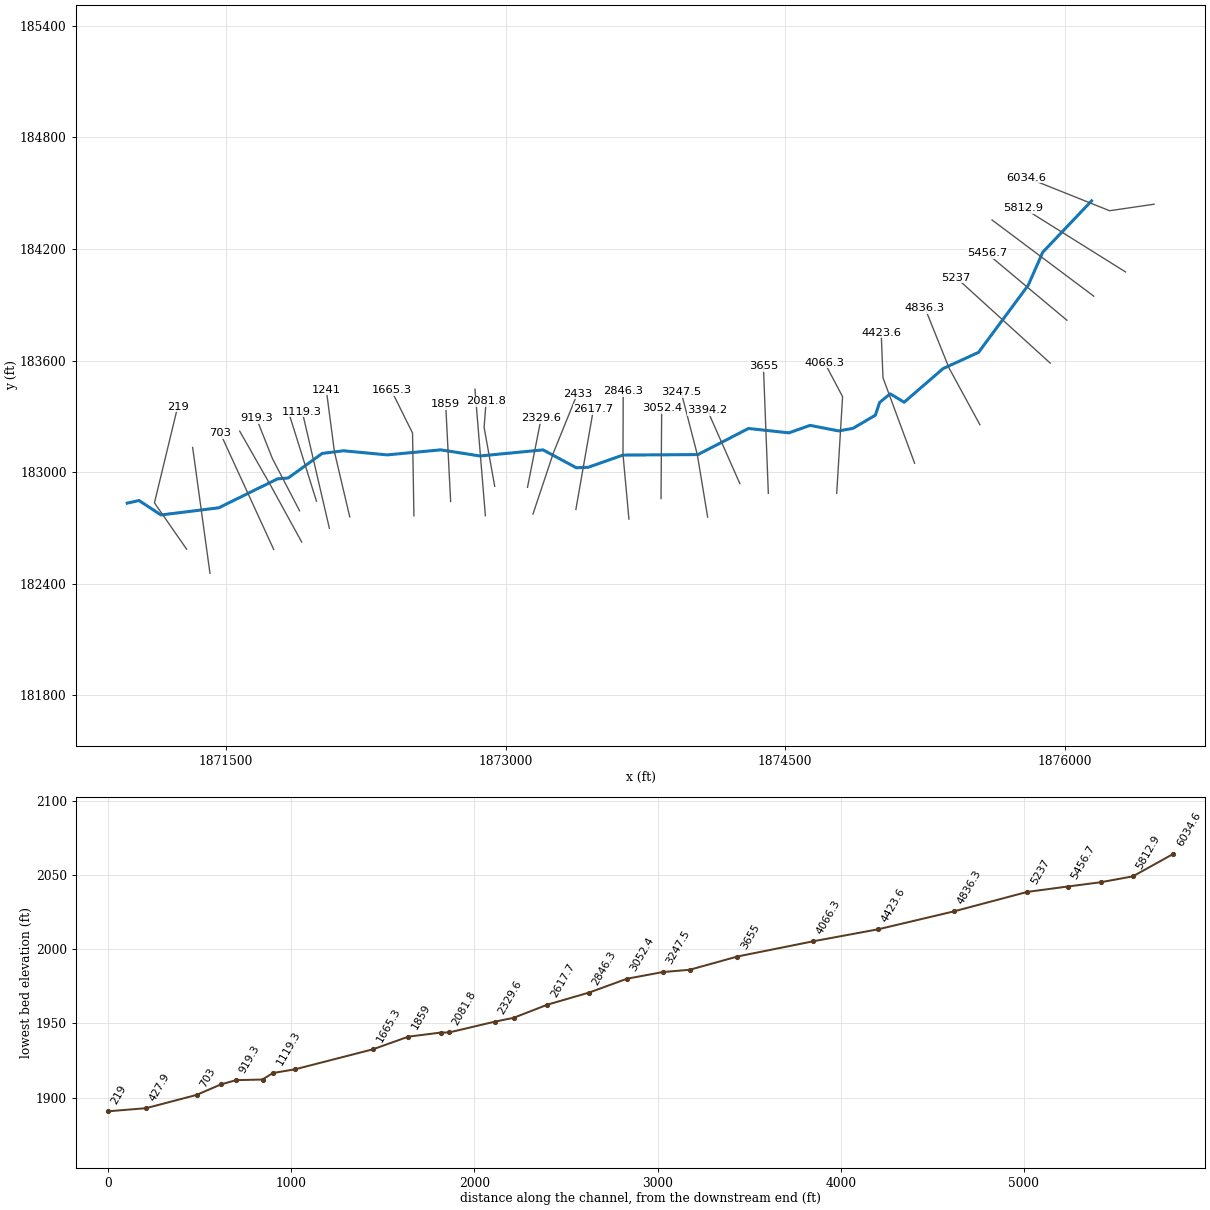
--- NosemanBr.prj (project) ---

Proj Title=NosemanBr
Current Plan=p01
Default Exp/Contr=0,0
English Units
Geom File=g01
Flow File=f01
Plan File=p01
BEGIN DESCRIPTION:
END DESCRIPTION:
DSS Export Rating Curves= 0
DSS Export Rating Curve Sorted= 0
DSS Export Volume Flow Curves= 0
DXF OffsetX= 0
DXF OffsetY= 0
DXF ScaleX= 0
DXF ScaleY= 0

--- NosemanBr.p01 (plan) ---

Plan Title=Floodplain
Program Version=4.00
Geom File=g01
Flow File=f01
K Sum by GR=0
Std Step Tol=0.01
Critical Tol=0.01
Num of Std Step Trials=20
Max Error Tol=0.3
Flow Tol Ratio=0.001
Split Flow NTrial=30
Split Flow Tol=0.02
Split Flow Ratio=0.02
Log Output Level=0
Friction Slope Method=1
Unsteady Friction Slope Method=2
Unsteady Bridges Friction Slope Method=1
Global Log Level=0
CheckData=False
Run HTab=0
Run UNet=0
Run PostProcess=0
UNET Theta=0
UNET Theta Warmup=0
UNET ZTol=0
UNET ZSATol=0
UNET MxIter=0
UNET MaxInSteps=0
UNET DtIC=0
UNET DtMin=0
UNET MaxCRTS=0
UNET WFStab=0
UNET SFStab=0
UNET WFX=0
UNET SFX=0
UNET DSS MLevel=0
UNET DZMax Abort=0
UNET Convert EG Bridges=0
UNET Use Existing IB Tables=0
UNET Froude Limit=0
UNET Froude Power=0
Write IC File=0
Echo Input=False
Echo Output=False
Write Detailed=0

--- NosemanBr.f01 (steady flow) ---

Flow Title=NFF Regression Equation
Program Version=4.00
Number of Profiles=1
Profile Names=P100yr
River Rch & RM=NosemanBr,Main      ,6034.6
684.6036
River Rch & RM=NosemanBr,Main      ,4836.3
710.0128
River Rch & RM=NosemanBr,Main      ,4423.6
774.5680
River Rch & RM=NosemanBr,Main      ,3655
785.9919
River Rch & RM=NosemanBr,Main      ,219
857.6130
Boundary for River Rch & Prof#=NosemanBr,Main      ,1
Up Type=0
Dn Type=3
Dn Slope=0.034063

--- NosemanBr.g01 (geometry) ---

Geom Title=USGS 10m DEM
Program Version=4.00

River Reach=NosemanBr       ,Main
Reach XY= 30
     1876145.254      184458.245     1875883.046        184182.1
     1875805.298      184004.985     1875538.524      183643.891
     1875348.302      183556.743     1875139.057       183375.81
     1875064.296      183420.933     1875007.229      183374.483
      1874984.87      183306.202     1874864.784      183235.577
     1874788.695      183221.421     1874634.049      183251.381
     1874520.539      183211.226     1874303.616      183234.677
      1874032.23      183094.458     1873629.398      183091.625
     1873442.962      183025.962     1873379.644      183023.617
     1873200.797      183119.663     1872862.548      183086.935
     1872651.488      183119.766     1872363.582      183092.689
     1872129.565      183114.808     1872015.431      183100.652
     1871833.046      182968.507     1871775.591      182963.817
     1871460.478       182808.31     1871150.141      182769.754
     1871032.277      182847.426     1870969.146      182833.233

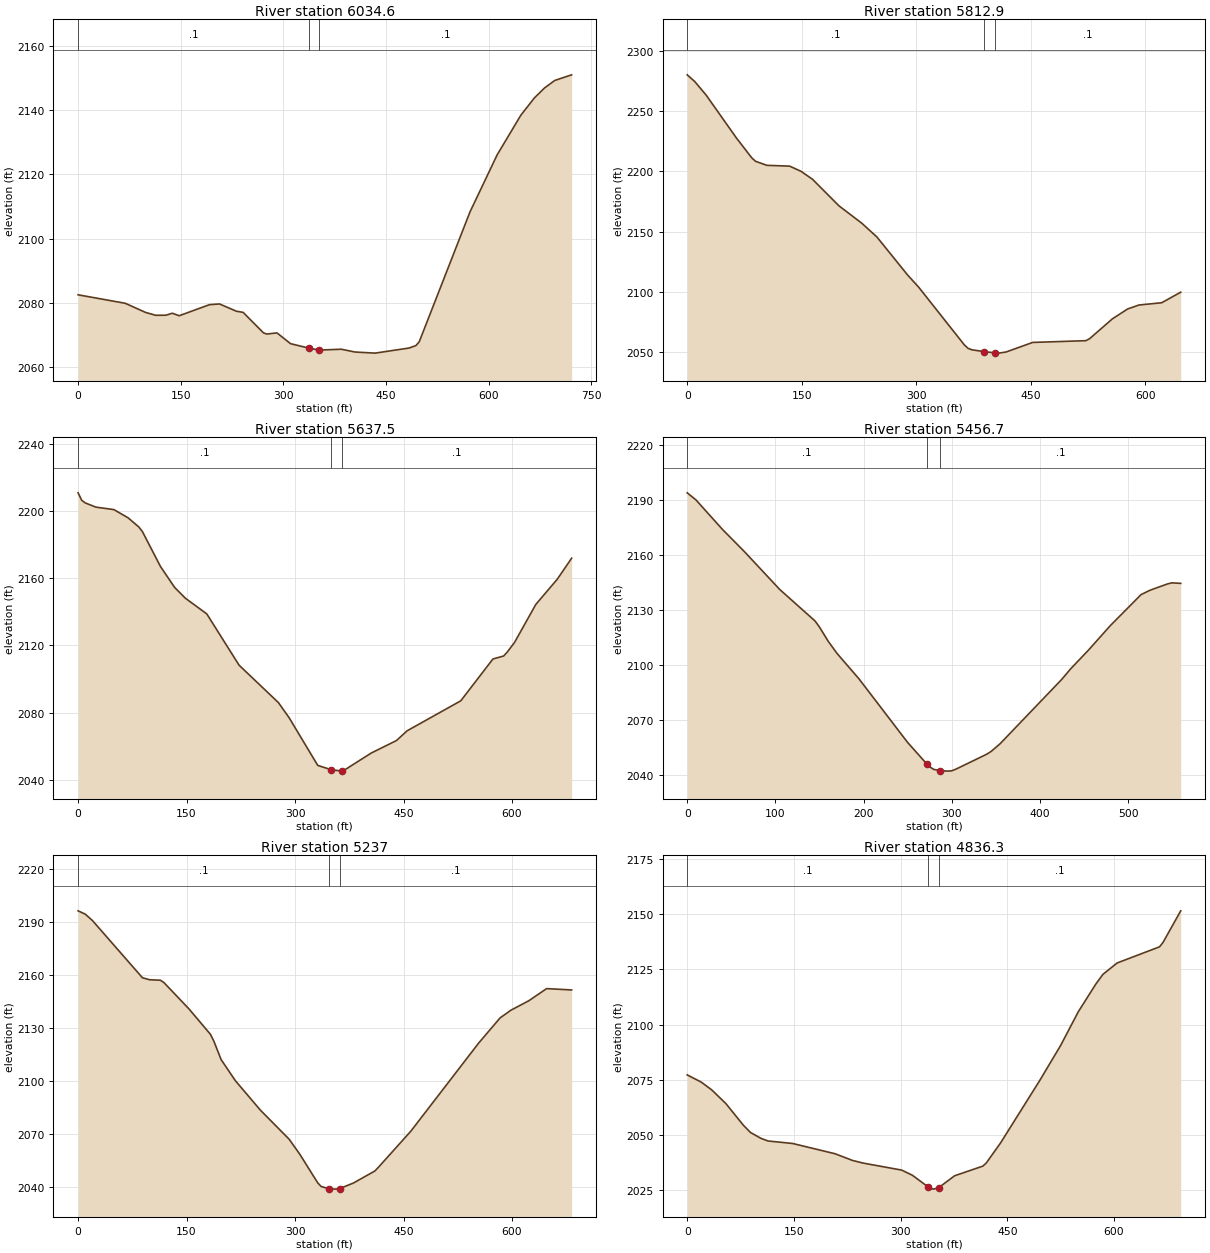
Type RM Length L Ch R = 1 ,6034.6  ,226.5,221.6,216.6
XS GIS Cut Line= 3
     1876480.627      184440.219        1876242.      184405.174
     1875796.302      184583.743
#Sta/Elev= 30
       0 2082.45    68.9  2079.8    98.4 2076.97   113.2 2076.06     128 2076.07
   137.8  2076.7   147.7 2075.91     192 2079.37   206.7 2079.59   231.3 2077.33
   241.2 2076.97   270.9 2070.58   275.8 2070.21   290.7 2070.56   310.5  2067.2
   337.6 2065.79   352.6  2065.2   384.7 2065.47   404.5  2064.6   434.2 2064.25
   483.7 2065.84   493.6 2066.59   498.6  2067.8   572.8 2108.33   612.4 2126.09
   647.1 2138.49   666.9 2143.88   681.7 2146.98   696.6 2149.32   721.3 2151.08
#Mann= 3 , 0 , 0
       0      .1       0   337.6    .045       0   352.6      .1       0
Bank Sta=337.6,352.6
XS Rating Curve= 0 ,0
Exp/Cntr=0.3,0.1

Type RM Length L Ch R = 1 ,5812.9  ,177.4,175.5,173.5
XS GIS Cut Line= 2
     1876327.359      184076.186     1875779.639        184419.4
#Sta/Elev= 30
       0 2280.26     9.9  2274.7    24.9 2263.36    64.6 2227.68    84.5 2211.34
    89.5 2208.43   104.4 2205.08   134.2 2204.41   149.2 2200.06   164.1 2193.49
   198.9 2171.36   228.7 2156.99   248.6 2145.46   288.4 2114.18   303.3 2103.76
     363  2055.9   367.9 2053.03   372.9 2051.84   388.7 2050.35   403.7 2049.24
   407.7 2049.07   417.6    2050   452.5 2057.96   522.1 2059.41     527 2061.04
   556.9 2077.54   576.8 2085.73   591.7 2089.04   621.5 2090.93   646.4  2099.7
#Mann= 3 , 0 , 0
       0      .1       0   388.7    .045       0   403.7      .1       0
Bank Sta=388.7,403.7
XS Rating Curve= 0 ,0
Exp/Cntr=0.3,0.1

Type RM Length L Ch R = 1 ,5637.5  ,182,180.8,179.6
XS GIS Cut Line= 3
     1876156.911      183945.958      1875883.91      184150.708
      1875610.91      184355.457
#Sta/Elev= 30
       0 2210.79       5 2206.38     9.9 2204.78    24.7 2202.27    49.5 2200.81
    69.2  2195.9    84.1 2190.42      89 2187.68   113.8 2167.02   133.5 2154.47
   148.4 2148.03     178 2138.69   222.6 2108.19     277 2085.91   291.8 2076.91
   331.4 2048.51   350.4 2045.89   365.4 2045.12     366  2045.1   405.5  2055.9
   440.2 2063.29     455 2069.11   529.2 2086.96   573.7 2111.87   588.5 2113.64
   593.5 2116.01   603.4 2121.62     633 2144.36   662.7 2159.39   682.5 2171.87
#Mann= 3 , 0 , 0
       0      .1       0   350.4    .045       0   365.4      .1       0
Bank Sta=350.4,365.4
XS Rating Curve= 0 ,0
Exp/Cntr=0.3,0.1

Type RM Length L Ch R = 1 ,5456.7  ,220.6,219.7,218.7
XS GIS Cut Line= 2
     1876012.598      183816.553     1875584.025      184175.772
#Sta/Elev= 30
       0 2193.93      10 2190.04    39.9 2174.01    64.9 2161.84   104.8 2141.26
   144.8 2124.09   149.8 2120.81   159.8 2112.98   169.8 2106.35   194.7 2092.48
   249.6 2057.93   271.7 2045.98   274.6 2044.57   279.6  2043.1   286.7 2042.52
   294.6  2042.2   299.6 2042.36   304.6  2043.3   339.5 2051.45   344.5 2052.99
   354.5 2057.12   424.4 2092.23   434.4 2097.93   454.4 2108.04   479.3 2121.47
   514.3 2138.46   524.3  2140.8   544.2 2144.26   549.2 2144.85   559.2 2144.57
#Mann= 3 , 0 , 0
       0      .1       0   271.7    .045       0   286.7      .1       0
Bank Sta=271.7,286.7
XS Rating Curve= 0 ,0
Exp/Cntr=0.3,0.1

Type RM Length L Ch R = 1 ,5237    ,408.1,400.7,390.4
XS GIS Cut Line= 3
     1875923.053      183586.151     1875670.734      183815.905
     1875418.415      184045.658
#Sta/Elev= 30
       0 2196.42     9.9 2194.53    19.8 2190.94      89 2158.47    98.9 2157.34
   113.8 2157.06   118.7 2155.74   153.3 2140.81     183 2126.41   187.9 2122.38
   197.8 2112.05   217.6 2100.04   252.2 2083.35   291.8 2066.93   306.6 2058.39
   331.4 2042.15   336.3 2040.05   346.8 2038.85   356.1  2038.6   361.8 2038.92
   380.8 2042.06   410.5 2048.92   415.4 2051.03     460 2071.39   553.9  2121.4
   583.6 2135.71   598.4 2140.03   623.2  2145.4   647.9 2152.31   682.5 2151.55
#Mann= 3 , 0 , 0
       0      .1       0   346.8    .045       0   361.8      .1       0
Bank Sta=346.8,361.8
XS Rating Curve= 0 ,0
Exp/Cntr=0.3,0.1

Type RM Length L Ch R = 1 ,4836.3  ,417.6,412.7,410.3
XS GIS Cut Line= 3
     1875545.758      183254.858     1875380.434      183558.959
     1875251.033      183881.733
#Sta/Elev= 30
       0 2077.25    19.8 2073.96    34.6 2070.42    54.4 2064.24    79.1 2054.39
      89 2051.15   103.8 2048.47   113.7 2047.29   148.3 2046.16   207.7 2041.53
   232.4 2038.48   247.2 2037.29   301.6  2034.1   316.5 2031.78   338.6 2026.53
   346.1 2025.48   353.6 2026.14   375.9 2031.52   415.7 2035.91   420.6 2037.37
   440.5 2046.37   495.2 2074.46     525 2090.55   549.8 2105.81   574.6 2118.43
   584.6 2122.82   604.5 2127.95   664.1 2135.27     669 2137.26   693.9 2151.58
#Mann= 3 , 0 , 0
       0      .1       0   338.6    .045       0   353.6      .1       0
Bank Sta=338.6,353.6
XS Rating Curve= 0 ,0
Exp/Cntr=0.3,0.1

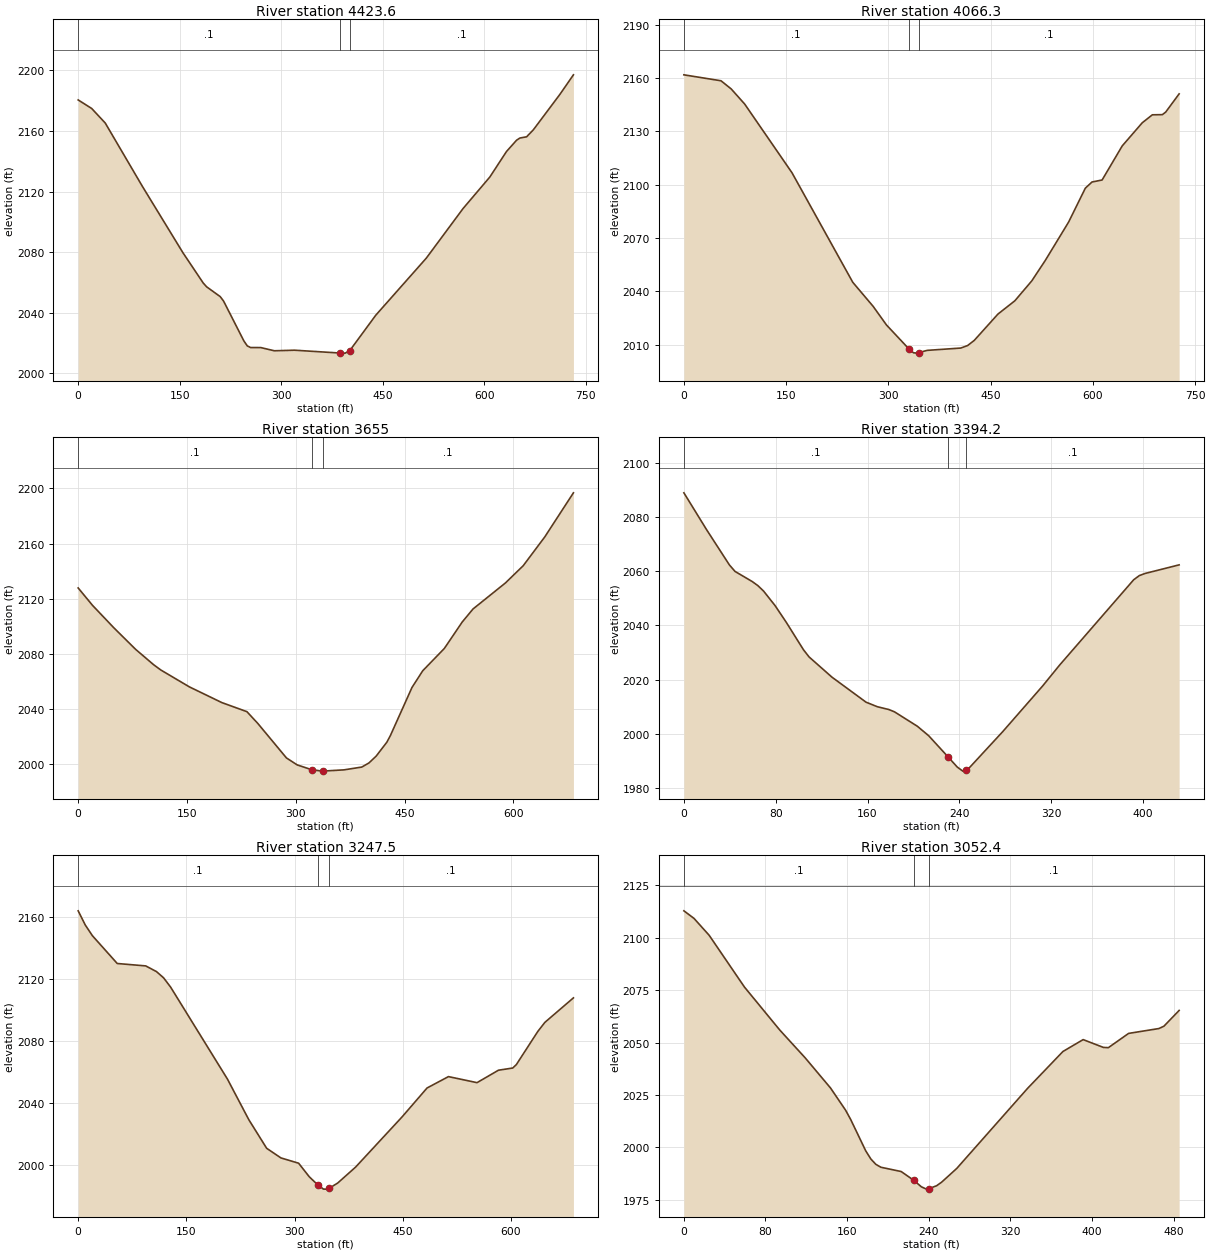
Type RM Length L Ch R = 1 ,4423.6  ,364.3,357.3,347.9
XS GIS Cut Line= 3
     1875195.328      183047.699     1875025.635      183507.127
     1875015.869      183749.037
#Sta/Elev= 30
       0 2180.49      20 2174.83      40 2165.25      95 2123.38   154.9 2079.61
   184.9 2059.63   189.9 2057.16   209.9 2050.72   214.9 2047.76   244.9 2021.47
   249.9 2018.21   254.9 2017.11   269.9 2017.09   289.9 2014.98   319.8 2015.36
   386.5  2013.5   389.8 2013.43   394.8 2013.45   401.5 2015.16   439.8 2038.44
   514.5 2076.11   568.8 2108.83   608.4 2129.64     633 2146.46   647.9 2153.92
   652.8 2155.34   662.7 2156.16   672.6 2160.73   712.1 2184.27   731.9 2197.05
#Mann= 3 , 0 , 0
       0      .1       0   386.5    .045       0   401.5      .1       0
Bank Sta=386.5,401.5
XS Rating Curve= 0 ,0
Exp/Cntr=0.3,0.1

Type RM Length L Ch R = 1 ,4066.3  ,408.5,411.4,414.2
XS GIS Cut Line= 3
     1874777.139      182886.449     1874808.681      183405.763
     1874712.395      183588.189
#Sta/Elev= 30
       0 2161.83    54.5 2158.48    69.4  2153.9    89.2 2145.39   158.6 2106.76
   247.8 2045.13   277.5 2031.68   297.3  2021.1   329.7 2007.85   336.9 2005.47
   341.9 2005.29   344.7  2005.6   356.8 2006.83   406.3 2008.15   416.2 2009.54
   426.1 2012.48   460.8 2027.26   485.6 2034.74   510.4 2045.92   530.1 2057.35
   564.5 2079.04     589 2098.08   598.8 2101.55   613.6 2102.67   643.1 2121.84
   672.5 2134.86   687.3 2139.34     702 2139.43   706.9 2140.88   726.6 2151.12
#Mann= 3 , 0 , 0
       0      .1       0   329.7    .045       0   344.7      .1       0
Bank Sta=329.7,344.7
XS Rating Curve= 0 ,0
Exp/Cntr=0.3,0.1

Type RM Length L Ch R = 1 ,3655    ,252.6,260.8,269
XS GIS Cut Line= 3
     1874410.144       182885.92     1874396.907      183227.195
     1874383.792      183568.143
#Sta/Elev= 30
       0  2127.8    19.8 2115.18    49.5 2098.76    79.2 2083.32   103.9 2072.24
   113.8  2068.4   153.4  2056.1     198 2044.75   232.6 2038.17   247.5 2029.71
   287.1 2004.64   301.9 1999.59     322 1996.09   336.6 1995.08     337 1995.09
   366.3 1995.99     391 1998.03   400.9 2001.04   410.8 2005.97   425.6 2016.11
   430.5 2020.98   460.2 2055.74     475 2067.82   504.7 2083.93   529.4 2103.12
   544.3 2112.58   588.8 2131.36   613.5 2143.93   643.2 2164.79   682.7 2196.74
#Mann= 3 , 0 , 0
       0      .1       0     322    .045       0     337      .1       0
Bank Sta=322,337
XS Rating Curve= 0 ,0
Exp/Cntr=0.3,0.1

Type RM Length L Ch R = 1 ,3394.2  ,152.4,146.7,143
XS GIS Cut Line= 2
     1874257.405      182938.067      1874083.13      183332.852
#Sta/Elev= 30
       0 2088.99    19.8 2075.36    39.7 2062.32    44.6 2059.94    59.5 2056.22
    64.5 2054.69    69.4  2052.7    79.4 2047.35    89.3 2041.08   104.2    2031
   109.1 2028.34     129 2020.88   158.7 2011.63   168.6 2009.94   178.6 2008.91
   183.5 2008.06   203.4 2002.74   213.3 1999.23   230.4 1991.31   238.1 1987.69
     243 1986.15   245.4 1986.58     248 1987.06   277.8 2000.74   312.5 2017.58
   327.4 2025.35   391.9 2056.86   396.8  2058.4   401.8 2059.19   431.5 2062.37
#Mann= 3 , 0 , 0
       0      .1       0   230.4    .045       0   245.4      .1       0
Bank Sta=230.4,245.4
XS Rating Curve= 0 ,0
Exp/Cntr=0.3,0.1

Type RM Length L Ch R = 1 ,3247.5  ,199,195.1,189.1
XS GIS Cut Line= 3
     1874084.386      182758.403     1874028.962      183094.101
     1873942.515      183429.729
#Sta/Elev= 30
       0 2163.65     9.9 2154.48    19.7 2147.66    54.2 2129.76    93.7 2128.21
   108.5 2124.58   118.4 2120.57   128.2 2114.57   207.1 2055.32   236.7 2029.22
   261.4 2010.87   281.1 2004.69   305.7 2001.28   320.5 1992.53   332.7 1987.15
   340.2 1984.61   345.2  1984.6   347.7 1985.02     360 1988.55   384.8 1998.81
   449.2 2031.08   483.8 2049.66   513.5 2056.99   553.1  2053.1   582.8  2061.1
   602.6 2062.51   607.6 2064.69   637.3 2085.97   647.2 2091.88   686.8 2107.65
#Mann= 3 , 0 , 0
       0      .1       0   332.7    .045       0   347.7      .1       0
Bank Sta=332.7,347.7
XS Rating Curve= 0 ,0
Exp/Cntr=0.3,0.1

Type RM Length L Ch R = 1 ,3052.4  ,203.9,206.1,206.5
XS GIS Cut Line= 2
     1873834.167      182858.043     1873837.724      183343.522
#Sta/Elev= 30
       0  2112.9     9.9  2109.3    24.8 2101.22    59.4 2076.52    94.1 2055.97
   118.9 2042.76   143.7 2028.41   158.5  2017.8   163.5 2013.36   178.3 1998.36
   183.3 1994.49   188.2 1991.94   193.2 1990.55     213 1988.52   225.3 1984.35
   232.8 1981.23   237.8 1980.12   240.3 1980.35   247.7 1981.73   252.6 1983.41
   267.5 1989.99   336.9 2028.18   371.6 2045.79   391.4 2051.46   411.2 2047.74
   416.1 2047.61     436 2054.42   465.7 2056.74   470.6 2057.86   485.5 2065.37
#Mann= 3 , 0 , 0
       0      .1       0   225.3    .045       0   240.3      .1       0
Bank Sta=225.3,240.3
XS Rating Curve= 0 ,0
Exp/Cntr=0.3,0.1

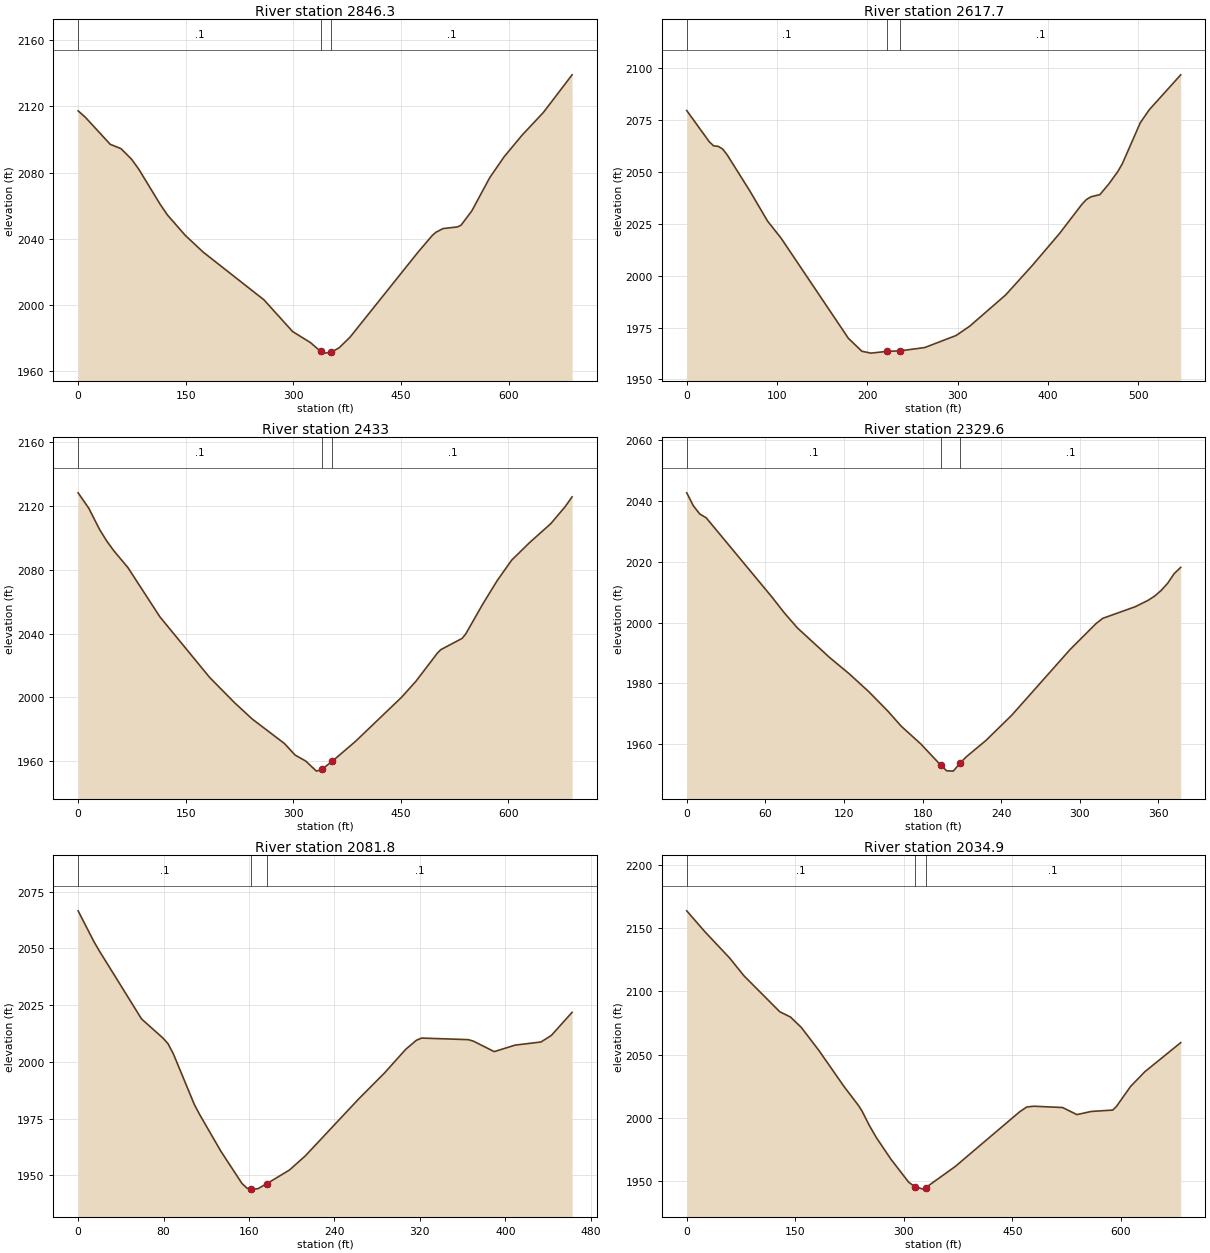
Type RM Length L Ch R = 1 ,2846.3  ,234.7,228.6,224.4
XS GIS Cut Line= 3
     1873661.892       182747.62     1873630.037       183094.87
     1873631.173       183434.44
#Sta/Elev= 30
       0 2117.28      10 2113.44    44.8 2097.04    59.8 2094.43    74.7 2087.92
    84.7  2081.9   114.6  2060.6   124.5 2054.33   149.4 2041.97   174.4 2031.84
     259 2003.03   298.9 1983.87   323.8 1977.19     338 1971.87   343.7 1970.83
     353 1971.46   363.7 1974.07   378.7 1980.39   473.6 2031.84   493.5 2041.97
   498.5 2043.87   508.5 2046.12   528.5 2047.11   533.5 2048.13   548.5 2056.74
   573.4 2076.78   593.4  2089.4   618.4 2102.47   648.3 2116.31   688.3 2139.05
#Mann= 3 , 0 , 0
       0      .1       0     338    .045       0     353      .1       0
Bank Sta=338,353
XS Rating Curve= 0 ,0
Exp/Cntr=0.3,0.1

Type RM Length L Ch R = 1 ,2617.7  ,188.2,184.7,179.7
XS GIS Cut Line= 2
     1873377.141      182799.359     1873471.391      183338.187
#Sta/Elev= 30
       0 2079.67    24.9 2064.66    29.8 2062.64    34.8 2062.41    39.8  2061.1
    44.8 2058.28    69.6  2041.1    89.5 2026.35   104.4 2018.16     179 1969.79
   193.9 1963.55   203.9 1962.64   221.6 1963.48   236.6 1963.76   263.6 1965.34
   298.4 1971.17   313.3 1975.63   353.1 1990.69   382.9 2005.06   412.7  2020.3
   437.6 2034.45   442.6 2036.75   447.6 2038.06   457.5 2039.12   467.4 2044.26
   477.4 2050.28   482.4 2054.06   502.2 2073.76   512.2 2080.08     547 2096.91
#Mann= 3 , 0 , 0
       0      .1       0   221.6    .045       0   236.6      .1       0
Bank Sta=221.6,236.6
XS Rating Curve= 0 ,0
Exp/Cntr=0.3,0.1

Type RM Length L Ch R = 1 ,2433    ,100.5,103.4,107.7
XS GIS Cut Line= 3
     1873146.835      182774.653     1873256.666      183104.003
     1873384.729      183420.727
#Sta/Elev= 30
       0 2128.16    14.9 2118.48    29.8 2105.33    39.7 2098.12    49.6 2091.98
    69.4 2081.34   114.1 2050.42   183.5 2012.44   218.2 1996.63     243 1986.34
   287.7 1971.08   302.5 1963.87   317.4 1960.08   332.3 1953.77   339.7  1954.8
   354.7 1960.08   386.8 1972.43   451.2 2000.14     471 2010.06   500.7 2027.56
   505.6 2029.84   535.3 2036.92   540.3 2039.59     565 2059.02   584.8 2073.46
   604.6    2086   629.4 2096.92   659.1 2108.85   678.9 2119.36   688.8 2125.62
#Mann= 3 , 0 , 0
       0      .1       0   339.7    .045       0   354.7      .1       0
Bank Sta=339.7,354.7
XS Rating Curve= 0 ,0
Exp/Cntr=0.3,0.1

Type RM Length L Ch R = 1 ,2329.6  ,239.4,247.9,256.3
XS GIS Cut Line= 2
     1873117.508      182918.506     1873190.418      183288.394
#Sta/Elev= 30
       0 2042.66       5 2038.44     9.9 2035.72    14.9 2034.43    64.5 2008.68
    74.4 2003.24    84.3 1998.32   109.1  1988.5     124 1983.17   138.9 1977.31
   153.8 1970.76   163.7 1965.94   178.6 1960.12   193.8 1953.16   198.4 1951.28
   203.4 1951.17   208.8 1953.88   213.3 1955.86   228.2  1961.2     248 1969.53
   292.7 1991.21   312.5 1999.72   317.5  2001.4   342.3 2005.22   352.2 2007.34
   357.2 2008.75   362.1 2010.57   367.1 2012.97     372 2016.09     377 2018.15
#Mann= 3 , 0 , 0
       0      .1       0   193.8    .045       0   208.8      .1       0
Bank Sta=193.8,208.8
XS Rating Curve= 0 ,0
Exp/Cntr=0.3,0.1

Type RM Length L Ch R = 1 ,2081.8  ,49,46.9,44.7
XS GIS Cut Line= 3
     1872941.455      182923.841     1872884.549       183240.38
     1872895.219      183380.867
#Sta/Elev= 30
       0 2066.57    14.8    2053    19.8 2048.96    59.4 2018.93    79.2 2010.61
    84.1 2008.09    89.1 2003.63   108.8 1981.25   113.8  1976.8   133.6 1960.69
   153.4 1946.44   158.3 1944.29   161.4 1944.08   163.3 1943.94   168.2  1944.1
   176.4 1946.27   197.9 1952.36   212.8 1958.63   262.2 1983.44     287 1995.19
   306.8 2005.58   316.7 2009.53   321.6  2010.5   365.3 2009.81   370.2 2009.13
   389.6 2004.53   409.1 2007.39   433.4 2008.78   443.1 2011.67   462.5 2021.85
#Mann= 3 , 0 , 0
       0      .1       0   161.4    .045       0   176.4      .1       0
Bank Sta=161.4,176.4
XS Rating Curve= 0 ,0
Exp/Cntr=0.3,0.1

Type RM Length L Ch R = 1 ,2034.9  ,176.4,176,175.5
XS GIS Cut Line= 3
     1872891.384      182765.583     1872863.378      183105.682
     1872835.372      183445.781
#Sta/Elev= 30
       0 2163.47    24.7 2147.22    59.4 2126.15    79.1 2112.17   128.6 2083.81
   143.4 2079.64   158.3 2071.45     183 2052.98   217.6  2024.6   237.4 2009.76
   242.3 2005.36   252.2 1994.18   262.1 1984.43   281.9 1967.63   306.6 1949.34
     315 1945.83   326.4 1943.84     330 1944.94   370.9 1961.66     460 2004.89
   469.8 2008.65   479.7 2009.26   519.3 2008.24   539.1 2002.65   558.9 2005.14
   588.5 2006.22   593.5 2008.93   613.3 2024.93     633 2036.51   682.5 2059.46
#Mann= 3 , 0 , 0
       0      .1       0     315    .045       0     330      .1       0
Bank Sta=315,330
XS Rating Curve= 0 ,0
Exp/Cntr=0.3,0.1

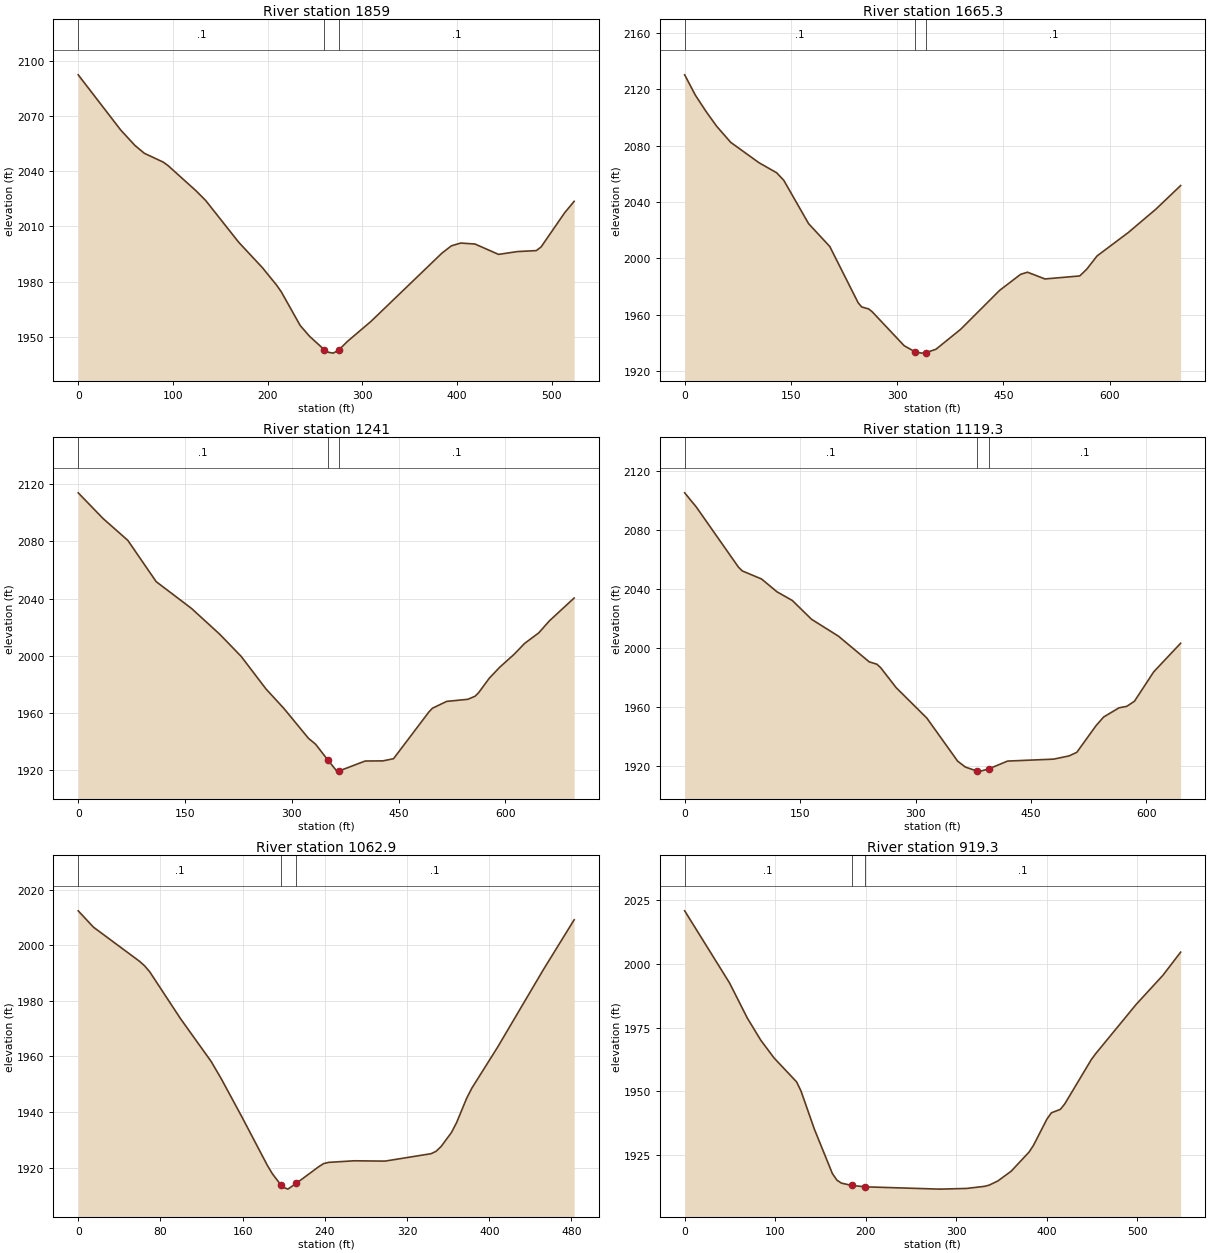
Type RM Length L Ch R = 1 ,1859    ,194.6,193.7,192.8
XS GIS Cut Line= 2
      1872704.94      182842.038     1872678.265      183364.862
#Sta/Elev= 30
       0 2092.45    44.9 2062.42    59.8 2054.08    69.8 2049.78    89.7 2044.99
    94.7 2043.15   124.6 2029.27   134.6 2024.08   169.5 2001.34   194.4 1987.59
   209.4  1978.1   214.4  1974.4   234.3 1956.14   244.3  1950.2   259.8 1942.94
   264.2 1941.55   269.2  1941.1   274.8 1942.67   284.2 1947.47   309.1 1958.39
   383.9 1995.46   393.9 1999.45   403.8 2000.97   418.8 2000.44   443.7  1994.8
   463.7 1996.33   483.6 1996.86   488.6 1998.84   513.5 2017.46   523.5 2023.65
#Mann= 3 , 0 , 0
       0      .1       0   259.8    .045       0   274.8      .1       0
Bank Sta=259.8,274.8
XS Rating Curve= 0 ,0
Exp/Cntr=0.3,0.1

Type RM Length L Ch R = 1 ,1665.3  ,419.4,424.3,427
XS GIS Cut Line= 3
     1872507.709       182765.57     1872500.434      183210.149
     1872387.033       183438.89
#Sta/Elev= 30
       0 2130.38      15 2115.99      30 2104.46      45 2093.92      65 2082.37
   104.9 2067.91   129.9 2060.74   139.9 2055.39   174.9  2024.6   204.8 2008.37
   244.8 1968.42   249.8 1965.41   259.8 1963.96   264.8 1961.91   309.8 1937.84
   325.6  1933.4   334.7 1932.57   340.6 1932.91   354.7 1935.32   389.7 1949.59
   444.6  1977.2   474.1 1988.55   483.9 1990.08   508.5  1985.3   557.6 1987.43
   567.4 1992.16   582.1 2001.66   626.3 2018.34   665.6 2035.12     700 2051.67
#Mann= 3 , 0 , 0
       0      .1       0   325.6    .045       0   340.6      .1       0
Bank Sta=325.6,340.6
XS Rating Curve= 0 ,0
Exp/Cntr=0.3,0.1

Type RM Length L Ch R = 1 ,1241    ,122.2,121.6,123.4
XS GIS Cut Line= 3
      1872163.29      182759.724     1872081.333      183108.471
     1872037.271      183443.839
#Sta/Elev= 30
       0 2114.03    34.8 2096.09    69.7 2080.72   109.5 2051.82   159.2 2033.03
     199 2014.87   228.9 1999.46   263.7 1976.68   288.6 1963.18   323.4 1942.09
   333.4 1937.97   350.7 1926.85   363.2 1919.12   365.7 1919.12     403  1926.2
   427.9  1926.3   442.8  1927.8   492.6 1960.62   497.5 1963.17   517.4 1967.95
   547.3 1969.44   557.2 1971.54   562.2 1973.96   577.1 1984.07     592 1991.91
   611.9  2000.8   626.9 2008.55   646.8 2015.95   661.7 2024.35   696.5 2040.37
#Mann= 3 , 0 , 0
       0      .1       0   350.7    .045       0   365.7      .1       0
Bank Sta=350.7,365.7
XS Rating Curve= 0 ,0
Exp/Cntr=0.3,0.1

Type RM Length L Ch R = 1 ,1119.3  ,54.3,56.4,57.2
XS GIS Cut Line= 2
     1872054.078      182697.995     1871908.256      183325.739
#Sta/Elev= 30
       0 2105.12      15 2095.59    69.9 2054.78    74.9 2052.21    99.9 2046.76
   119.9  2038.1   139.9 2032.19   164.9 2019.45   199.8 2008.04   239.8 1990.63
   249.8 1989.03   254.8 1986.63   274.8 1973.16   314.7 1952.55   354.7 1923.39
   364.7 1919.39   379.9 1916.62   384.7 1916.61   394.9 1918.09   419.6 1923.41
   479.6 1924.74   499.6 1926.93   509.6 1929.34   534.6 1947.43   544.5 1953.29
   564.5  1959.5   574.5 1960.49   584.5 1963.94   609.5 1983.83   644.5 2003.23
#Mann= 3 , 0 , 0
       0      .1       0   379.9    .045       0   394.9      .1       0
Bank Sta=379.9,394.9
XS Rating Curve= 0 ,0
Exp/Cntr=0.3,0.1

Type RM Length L Ch R = 1 ,1062.9  ,140,143.6,149.1
XS GIS Cut Line= 2
     1871984.724      182843.817     1871840.681      183304.399
#Sta/Elev= 30
       0 2012.47    14.9 2006.57    59.7 1994.28    64.7 1992.63    69.6  1990.5
    99.5 1973.66   129.4 1958.19   139.3 1951.92   159.2  1938.3   184.1 1920.75
     189 1917.73     197 1913.84     199 1912.99     204 1912.22     212 1914.25
   233.8 1920.23   238.8 1921.42   243.8 1921.86   268.6 1922.43   298.5 1922.31
   343.3 1924.98   348.2 1925.83   353.2  1927.6   363.2 1932.62   368.2 1936.19
   378.1 1945.04   383.1 1948.63     408 1963.28   452.7 1991.31   482.6 2009.24
#Mann= 3 , 0 , 0
       0      .1       0     197    .045       0     212      .1       0
Bank Sta=197,212
XS Rating Curve= 0 ,0
Exp/Cntr=0.3,0.1

Type RM Length L Ch R = 1 ,919.3   ,81.8,81.3,80.5
XS GIS Cut Line= 3
      1871894.03      182792.246     1871748.208      183073.219
     1871662.849      183288.394
#Sta/Elev= 30
       0 2020.66    49.5  1992.5    69.2 1978.73    84.1 1970.06    98.9 1963.06
   123.7 1953.74   128.6 1950.13   143.4 1935.18   163.2 1917.91   168.2 1915.33
   173.1 1914.17   184.5 1913.26   199.5 1912.71   281.9 1911.81   311.6 1912.08
   331.3  1912.9   336.3 1913.35   346.1 1915.01   360.9 1918.86   380.6 1926.34
   385.5 1928.99   400.3 1939.22   405.2 1941.66   415.1    1943     420 1945.15
   449.5 1962.58   454.5 1964.93   498.8 1984.03   528.4 1995.43     548 2004.49
#Mann= 3 , 0 , 0
       0      .1       0   184.5    .045       0   199.5      .1       0
Bank Sta=184.5,199.5
XS Rating Curve= 0 ,0
Exp/Cntr=0.3,0.1

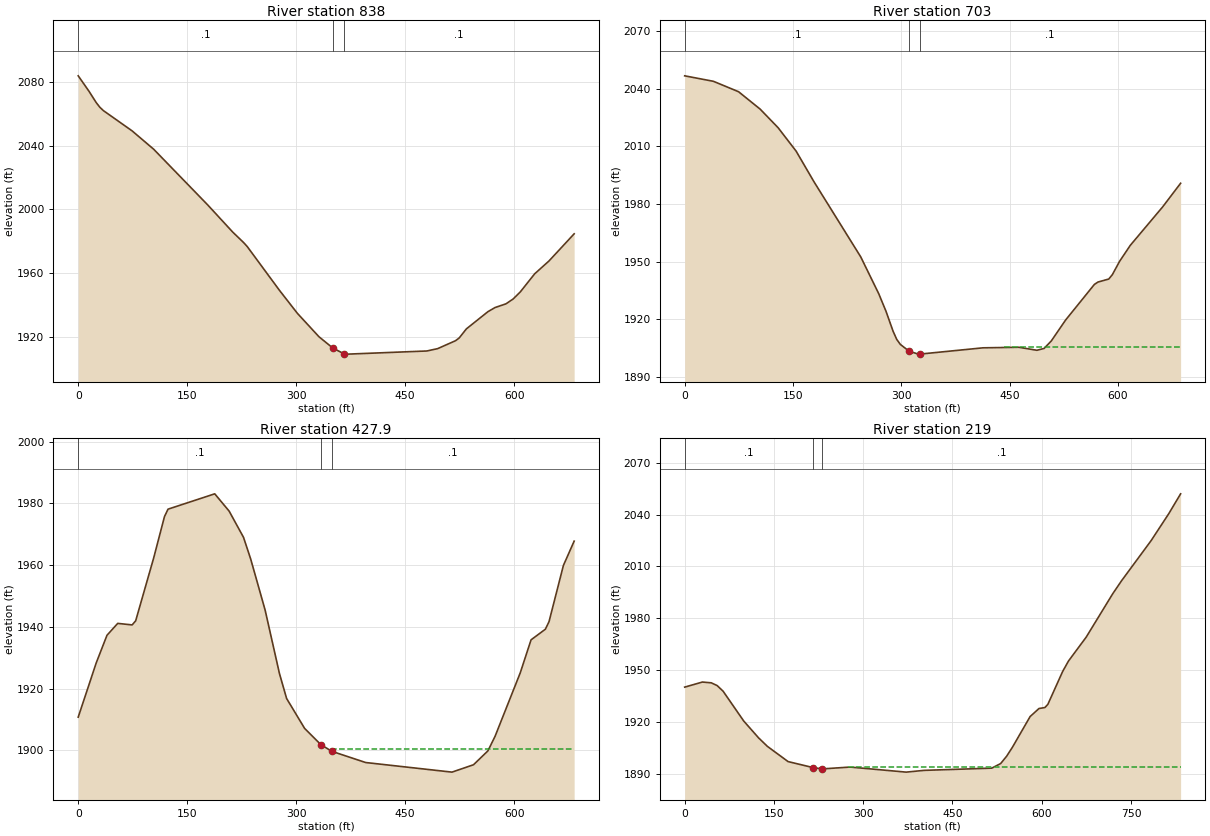
Type RM Length L Ch R = 1 ,838     ,135.3,135,134.3
XS GIS Cut Line= 3
     1871905.287      182624.367     1871741.343      182923.717
     1871572.627      183220.331
#Sta/Elev= 30
       0 2083.77    14.8 2074.11    24.7 2067.01    29.7 2064.08    34.6 2061.95
    74.2  2049.2   103.9 2037.67   178.1 2002.77   212.7 1985.64   227.5 1979.14
   232.5 1976.65     277 1949.07   301.7 1934.61   331.4 1919.92   350.7 1912.76
   365.7 1909.29     371 1909.04   479.8 1911.01   494.6 1912.48   519.3 1917.47
   524.3 1919.19   534.2 1924.89   563.8 1935.68   573.7  1938.3   588.6 1940.61
   598.5 1943.64   608.4 1948.11   628.1 1959.43   647.9 1967.54   682.5 1984.57
#Mann= 3 , 0 , 0
       0      .1       0   350.7    .045       0   365.7      .1       0
Bank Sta=350.7,365.7
XS Rating Curve= 0 ,0
Exp/Cntr=0.3,0.1

Type RM Length L Ch R = 1 ,703     ,281.5,275.1,268.6
XS GIS Cut Line= 2
     1871755.322      182584.183     1871469.014      183208.371
#Sta/Elev= 30
       0 2046.71    39.8 2043.86    74.6 2038.44   104.5 2029.38   129.4 2019.69
   154.3 2007.52   179.1 1991.54   243.8 1952.46   268.7 1933.31   278.7 1924.23
   288.6 1913.74   293.6 1909.54   298.6 1906.93   310.6 1903.43   323.4 1901.86
   325.6 1901.87     413 1905.14   462.8 1905.43   487.7 1903.86   497.6 1904.81
   507.6  1908.7   527.5 1919.63   567.3 1938.14   572.3 1939.38   587.2 1940.94
   592.2 1943.24   602.1  1950.1     617 1958.47   661.8 1978.48   686.7  1990.8
#Mann= 3 , 0 , 0
       0      .1       0   310.6    .045       0   325.6      .1       0
#XS Ineff= 2 , 0
                          442.69         1905.49
Permanent Ineff=
       F       F
Bank Sta=310.6,325.6
XS Rating Curve= 0 ,0
Exp/Cntr=0.3,0.1

Type RM Length L Ch R = 1 ,427.9   ,195.9,208.9,226
XS GIS Cut Line= 3
     1871413.059      182456.517     1871366.606       182794.59
     1871320.153      183132.663
#Sta/Elev= 30
       0 1910.74    24.7 1928.26    39.6 1937.27    54.4 1941.12    74.2 1940.62
    79.1 1941.96   103.9 1962.35   118.7  1975.7   123.6 1978.12   187.9 1983.09
   207.7 1977.49   227.5 1968.99   237.4 1961.94   257.2 1945.46     277 1924.82
   286.8 1916.78   311.6 1907.09   333.8 1901.87   348.8 1899.69   395.6 1896.04
   514.4 1892.93     544 1895.32   563.8 1899.81   573.7 1904.55   608.3 1925.08
   623.2 1935.79   642.9 1939.23   647.9 1941.66   667.7 1959.88   682.5 1967.76
#Mann= 3 , 0 , 0
       0      .1       0   333.8    .045       0   348.8      .1       0
#XS Ineff= 2 , 0
                          351.55         1900.58
Permanent Ineff=
       F       F
Bank Sta=333.8,348.8
XS Rating Curve= 0 ,0
Exp/Cntr=0.3,0.1

Type RM Length L Ch R = 1 ,219     ,228.3,219,205.1
XS GIS Cut Line= 3
     1871287.626      182585.962      1871115.13      182834.925
     1871239.612      183350.635
#Sta/Elev= 30
       0 1940.05    29.8 1942.99    44.7 1942.54    54.6 1940.94    64.6 1937.68
    99.3 1920.39   124.1  1910.7     139 1905.74   173.8 1896.92   215.6 1893.46
   230.6 1892.68   278.1 1893.75   372.3 1890.82     402 1891.83   516.1 1893.13
     531 1895.79   540.9 1899.97   550.8 1905.25   580.5 1923.01   595.4 1927.66
   605.3 1928.23   610.3 1930.07   635.1 1949.07     645 1955.18   674.7 1968.99
   719.4 1994.17   734.2 2001.68   783.8 2024.88   813.6 2040.56   833.4    2052
#Mann= 3 , 0 , 0
       0      .1       0   215.6    .045       0   230.6      .1       0
#XS Ineff= 2 , 0
                          275.17         1893.72
Permanent Ineff=
       F       F
Bank Sta=215.6,230.6
XS Rating Curve= 0 ,0
Exp/Cntr=0.3,0.1

Chan Stop Cuts=-1
Use User Specified Reach Order=0